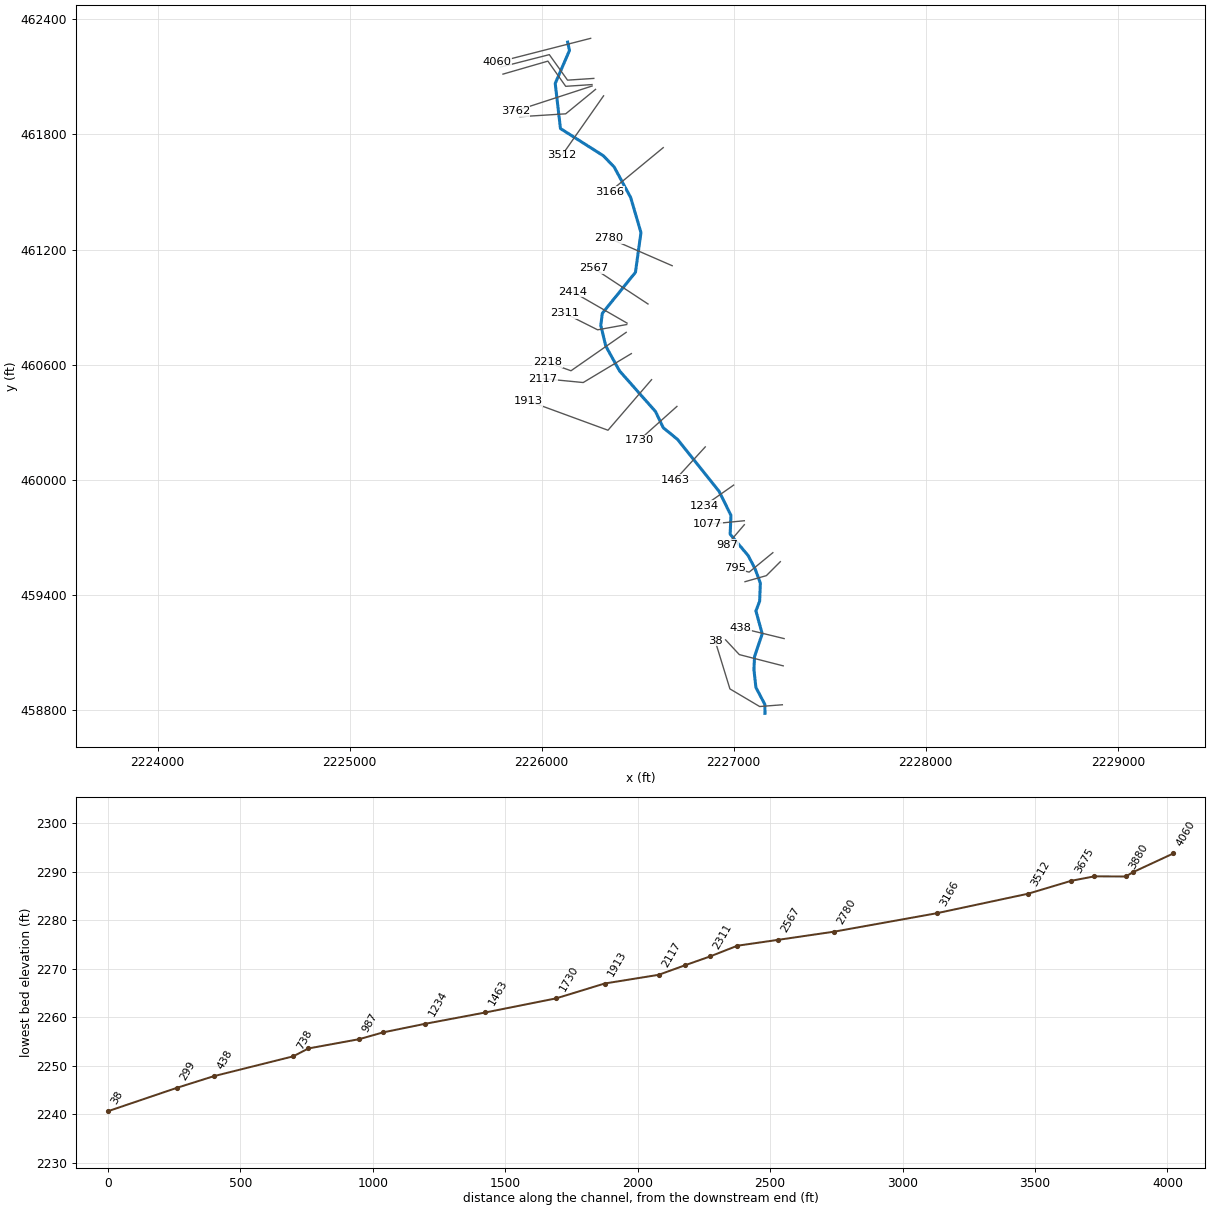
--- DRYCK1.prj (project) ---

Proj Title=DRYCK1
Current Plan=p01
Default Exp/Contr=0,0
English Units
Geom File=g01
Flow File=f01
Plan File=p01
Background Map Layer=Inundation Boundary (01pct Value_0)
BEGIN DESCRIPTION:
----------MODEL BY WOOD PLC 2021----------
Stream Name: Dry Creek II
Flood Zone: Enhanced Approximate
Pocahontas County, WV
HEC-RAS Version: RAS 6.1
Vertical Datum: NAVD88
Projection: NAD 1983 StatePlane West Virginia S FIPS 4702 (US Feet)
Terrain: 1-meter LIDAR (FEMA Region III 3DEP collected 2016-2018)
Land Use: 2019 NLCD
Hydrologic Method:
WV SIR2010-5033 regression equations
Model Notes:
Normal Depth tie in to Stony Creek
END DESCRIPTION:
DSS Export Rating Curves= 0
DSS Export Rating Curve Sorted= 0
DSS Export Volume Flow Curves= 0
DXF OffsetX= 0
DXF OffsetY= 0
DXF ScaleX= 0
DXF ScaleY= 0

--- DRYCK1.p01 (plan) ---

Plan Title=Floodplain
Program Version=6.10
Short Identifier=Floodplain
Geom File=g01
Flow File=f01
Subcritical Flow
K Sum by GR= 0
Std Step Tol= 0.01
Critical Tol= 0.01
Num of Std Step Trials= 20
Max Error Tol= 0.3
Flow Tol Ratio= 0.001
Split Flow NTrial= 30
Split Flow Tol= 0.02
Split Flow Ratio= 0.02
Log Output Level= 0
Friction Slope Method= 1
Unsteady Friction Slope Method= 2
Unsteady Bridges Friction Slope Method= 1
Parabolic Critical Depth
Global Vel Dist= 0 , 0 , 0
Global Log Level= 0
CheckData=True
Encroach Param=-1 ,0,0, 0
Mapping Interval=1HOUR
Computation Time Step Use Courant=        0
Computation Time Step Use Time Series=    0
Computation Time Step Count To Double=0
Computation Time Step Max Doubling=0
Computation Time Step Max Halving=0
Computation Time Step Residence Courant=0
Run HTab= 0
Run UNet= 0
Run Sediment= 0
Run PostProcess= 0
Run WQNet= 0
Run RASMapper=-1
UNET Theta= 0
UNET Theta Warmup= 0
UNET ZTol= 0
UNET ZSATol= 0
UNET MxIter= 0
UNET Max Iter WO Improvement= 0
UNET MaxInSteps= 0
UNET DtIC= 0
UNET DtMin= 0
UNET MaxCRTS= 0
UNET WFStab= 0
UNET SFStab= 0
UNET WFX= 1
UNET SFX= 1
UNET Gravity=32.174
UNET 1D Methodology=Finite Difference
UNET DSS MLevel= 1
UNET Pardiso=0
UNET DZMax Abort= 0
UNET Use Existing IB Tables= 0
UNET Froude Reduction=False
UNET Froude Limit= 0
UNET Froude Power= 0
UNET D1 Cores= 0
UNET WindReference=Eulerian
UNET WindDragFormulation=Hsu (1988)
UNET D2 Coriolis=0
UNET D2 Cores= 0
UNET D2 Theta= 1
UNET D2 Theta Warmup= 1
UNET D2 Z Tol= 0.01
UNET D2 Volume Tol= 0.01
UNET D2 Max Iterations= 20
UNET D2 Equation= 0
UNET D2 RampUpFraction=0.1
UNET D2 TimeSlices= 1
UNET D2 Turbulence Formulation=Non-Conservative (original)
UNET D2 Eddy Viscosity=0.3
UNET D2 Transverse Eddy Viscosity=0.1
UNET D2 Smagorinsky Mixing=0
UNET D2 BCVolumeCheck=0
UNET D2 Cores=0
UNET D2 SolverType=PARDISO (Direct)
UNET D2 Minimum Iterations= 2147483647
UNET D2 Maximum Iterations= 2147483647
UNET D2 Restart Number= 10
UNET D2 Relaxation Coeff=1.3
UNET D2 SOR Precondition Iterations= 10
UNET D2 ILUT Maximum Fill= 8
UNET D2 ILUT Tolerance=1E-08
UNET D1D2 MaxIter= 0
UNET D1D2 ZTol=0.01
UNET D1D2 QTol=0.1
UNET D1D2 MinQTol=1
Write IC File= 0
Write IC File at Fixed DateTime=0
Write IC File at Sim End=0
Echo Input=False
Echo Parameters=False
Echo Output=False
Write Detailed= 0
HDF Write Warmup=0
HDF Write Time Slices=0
HDF Flush=0
HDF Compression= 1
HDF Chunk Size= 1
HDF Spatial Parts= 1
HDF Use Max Rows=0
HDF Fixed Rows= 1
Calibration Method= 0
Calibration Iterations= 20
Calibration Max Change=0.05
Calibration Tolerance=0.2
Calibration Maximum=1.5
Calibration Minimum=0.5
Calibration Optimization Method= 1
WQ AD Non Conservative
WQ ULTIMATE=-1
WQ Max Comp Step=1HOUR
WQ Output Interval=15MIN
WQ Output Selected Increments= 0
WQ Output face flow=0
WQ Output face velocity=0
WQ Output face area=0
WQ Output face dispersion=0
WQ Output cell volume=0
WQ Output cell surface area=0
WQ Output cell continuity=0
WQ Output cumulative cell continuity=0
WQ Output face conc=0
WQ Output face dconc_dx=0
WQ Output face courant=0
WQ Output face peclet=0
WQ Output face adv mass=0
WQ Output face disp mass=0
WQ Output cell mass=0
WQ Output cell source sink temp=0
WQ Output nsm pathways=0
WQ Output nsm derived pathways=0
WQ Create Restart=0
WQ Fixed Restart=0
WQ System Summary=0
WQ Write To DSS=0
Sorting and Armoring Iterations= 10
XS Update Threshold= 0.02
Bed Roughness Predictor= 0
Hydraulics Update Threshold= 0.02
Energy Slope Method= 1
Volume Change Method= 1
Sediment Retention Method= 0
Sediment TS Multiplier= 1
Warm Up Method= 0
XS Weighting Method= 0
Number of US Weighted Cross Sections= 1
Number of DS Weighted Cross Sections= 1
Upstream XS Weight=0
Main XS Weight=1
Downstream XS Weight=0
Number of DS XS's Weighted with US Boundary= 1
Upstream Boundary Weight= 1
Weight of XSs Associated with US Boundary= 0
Number of US XS's Weighted with DS Boundary= 1
Downstream Boundary Weight= 0.5
Weight of XSs Associated with DS Boundary= 0.5
Percentile Method= 0
Sediment Output Level= 3
Mass or Volume Output= 0
Output Increment Type= 1
Profile and TS Output Increment= 1
Transport Output Increment 1
XS Output Flag= 0
XS Output Increment= 10
Read HDF5 Sediment Hotstart= 0
Sediment Hotstart Type= 0
Write Gradation File= 0
Read Gradation Hotstart= 0
Write HDF5 File= 1
Write Binary Output= 1
Write DSS Sediment File= 0
DSS Sediment Output Type= 1
SV Curve= 0
Specific Gage Flag= 0
Subcell Erosion Methods= 0
Subcell Deposition Methods= 0
Advection Scheme= 1
Matrix Solver= 0
Implicit Weighting Factor= 1
Maximum Outer Loop Convergence Iterations= 5
Convergence Maximum Absolute= 0.001
Convergence RMSE= 0.0001
Grain Fractions Max Abs Error= 0.001
Max Subgrid Regions= 1
Max Subgrid Length Scale= 3.402823E+38
Initial Layer Thickness= 3.402823E+38
Min Layer Thickness= 3.402823E+38
Max Layer Thickness= 3.402823E+38
Number of Layers= 5

--- DRYCK1.f01 (steady flow) ---

Flow Title=Flow
Program Version=6.10
Number of Profiles= 6
Profile Names=01pct,10pct,04pct,02pct,0_2pct,01plus
River Rch & RM=DRYCK1,Main,4060
     589     312     414     499     822     871
Boundary for River Rch & Prof#=DRYCK1,Main            , 1
Up Type= 0
Dn Type= 3
Dn Slope=0.0197
Boundary for River Rch & Prof#=DRYCK1,Main            , 2
Up Type= 0
Dn Type= 3
Dn Slope=0.0197
Boundary for River Rch & Prof#=DRYCK1,Main            , 3
Up Type= 0
Dn Type= 3
Dn Slope=0.0197
Boundary for River Rch & Prof#=DRYCK1,Main            , 4
Up Type= 0
Dn Type= 3
Dn Slope=0.0197
Boundary for River Rch & Prof#=DRYCK1,Main            , 5
Up Type= 0
Dn Type= 3
Dn Slope=0.0197
Boundary for River Rch & Prof#=DRYCK1,Main            , 6
Up Type= 0
Dn Type= 3
Dn Slope=0.0197
DSS Import GetInterval= 0
DSS Import GetPeak= 0
DSS Import FillOption= 0

--- DRYCK1.g01 (geometry) ---

Geom Title=Geometry
Program Version=6.10

River Reach=DRYCK1          ,Main
Reach XY= 30
     2226135.533       462279.73     2226145.128      462236.561
     2226070.849       462064.67     2226098.116      461829.889
      2226321.17      461688.423     2226377.945      461629.556
2226463.71396023461470.828117772     2226517.283       461288.23
      2226488.53      461081.125   2226316.24635460868.009857457
2226308.13266171460805.834961999     2226334.012      460697.368
2226405.55192942460568.1534689042226592.74073445460356.852265548
     2226633.719      460271.7942226708.16530084460210.886168065
     2226923.838      459941.164     2226985.889      459816.104
     2226981.718      459717.8932227076.69147694459604.573891042
     2227111.808      459536.417     2227138.852      459463.284
2227135.35136993459369.0768326432227115.88431515459318.121990401
2227148.65498994459198.884522331     2227108.787      459081.129
     2227105.557      459013.379     2227115.795      458919.739
     2227162.521      458831.372     2227163.105      458784.775

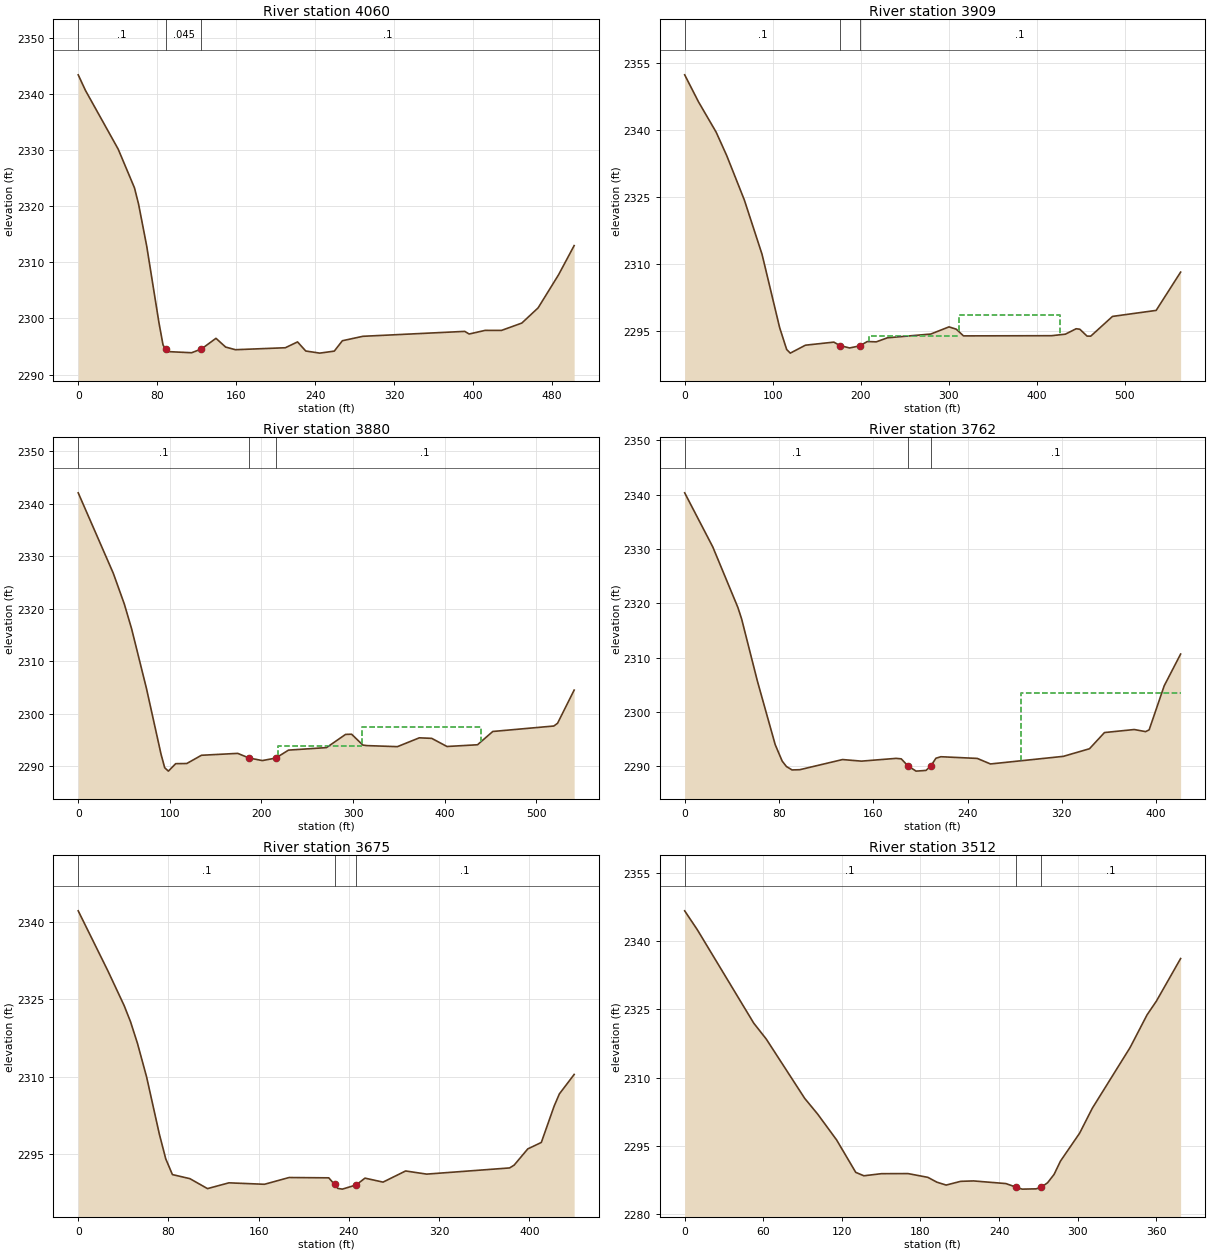
Type RM Length L Ch R = 1 ,4060    ,151.6,151.6,151.6
BEGIN DESCRIPTION:
structure xs 4
END DESCRIPTION:
XS GIS Cut Line= 2
2226255.37098427462299.6222478022225768.82999376462175.158273485
#Sta/Elev= 30
       0 2343.46     7.4 2340.66    40.5  2330.2      57 2323.29    61.1 2320.42
    69.4 2312.88    81.7 2299.31    85.9 2295.28   88.42 2294.54      90  2294.1
   114.8 2293.89  124.79 2294.56   139.5 2296.46   149.3  2294.9   159.2 2294.43
   209.7 2294.78   222.1 2295.82   230.4  2294.2   244.6 2293.82   259.3 2294.18
   267.5 2296.03   288.2 2296.82   391.4  2297.7   395.9 2297.23   412.1 2297.88
   428.6 2297.87   449.2 2299.18   465.7 2301.89   486.4 2307.79   502.2    2313
#Mann= 3 ,-1,0
       0      .1       0   88.42    .045       0  124.79      .1       0
Bank Sta=88.42,124.79
XS Rating Curve= 0 ,0
Exp/Cntr(USF)=0,0
Exp/Cntr=0.5,0.3

Type RM Length L Ch R = 1 ,3909    ,28.4,28.7,26.6
BEGIN DESCRIPTION:
structure xs 3; 10.7 ft between structure and xs
END DESCRIPTION:
XS GIS Cut Line= 4
2226271.86993681462090.9982500342226134.94372419462081.924826306
 2226040.0852034462214.7267554112225785.20448232462149.563075912
#Sta/Elev= 30
       0 2352.44    15.7 2346.38    35.8 2339.56    47.8  2334.3    67.8 2324.35
    87.9 2312.16   107.9 2295.71   115.9 2290.79     120 2289.98   137.2 2291.76
   169.5 2292.45   176.4 2291.68   187.4 2291.14   198.9 2291.61   207.5 2292.58
   217.7 2292.51   230.4 2293.42   279.6 2294.26   300.3 2295.87   308.6 2295.35
   316.8 2293.85   416.7 2293.89   432.5 2294.23   444.8 2295.45     449 2295.34
   457.2  2293.8   461.4 2293.79   486.1 2298.22   535.7 2299.57   563.5 2308.16
#Mann= 3 ,-1,0
       0      .1       0   176.4    .045       0   198.9      .1       0
#XS Ineff= 4 ,-1
       0     166 2291.37     209  311.32  2293.9  311.32  426.59  2298.6
  426.59   563.5  2293.9
Permanent Ineff=
       F       F       T       F
Bank Sta=176.4,198.9
XS Rating Curve= 0 ,0
Exp/Cntr(USF)=0,0
Exp/Cntr=0.5,0.3

Type RM Length L Ch R = 1 ,3880    ,93.1,118.3,137.4
BEGIN DESCRIPTION:
structure xs 2; 9 ft between structure and xs
END DESCRIPTION:
XS GIS Cut Line= 4
2226262.38408473462058.8288386362226125.45787211462049.755414908
2226032.66149308462180.9076306082225798.81461791462113.269381002
#Sta/Elev= 30
       0 2342.05    38.3 2326.73    50.3 2320.89    58.3 2316.15    74.4 2304.87
    90.4 2292.28    94.4 2289.71    98.4 2289.06   106.4 2290.48   118.5 2290.51
   134.5 2292.08   174.1 2292.44   186.5 2291.56   200.9 2291.07   215.6 2291.54
   229.5 2293.06     271 2293.54   291.8 2296.05   298.4 2296.09   310.7 2294.02
   315.1 2293.92   348.4 2293.72   372.3  2295.4   385.8  2295.3   402.5 2293.75
   435.8 2294.08   452.5 2296.61   519.1 2297.65   523.2 2298.17   541.3 2304.49
#Mann= 3 ,-1,0
       0      .1       0   186.5    .045       0   215.6      .1       0
#XS Ineff= 4 ,-1
       0   183.5 2291.37   218.6  309.97  2293.9  309.97  439.44  2297.5
  439.44   541.3  2293.9
Permanent Ineff=
       F       F       T       F
Bank Sta=186.5,215.6
XS Rating Curve= 0 ,0
Exp/Cntr(USF)=0,0
Exp/Cntr=0.5,0.3

Type RM Length L Ch R = 1 ,3762    ,90.7,86.7,83.3
BEGIN DESCRIPTION:
structure xs 1
END DESCRIPTION:
XS GIS Cut Line= 2
2226262.79651308462051.4051283132225862.74101236461921.077769316
#Sta/Elev= 30
       0 2340.32    23.8 2330.38    45.1 2319.24    48.3 2317.11    61.7 2305.65
    76.8 2293.96    82.7 2290.94    86.3 2289.94    91.1 2289.31    97.6 2289.35
   133.9 2291.22     150 2290.93   179.4 2291.44   183.7 2291.35  189.542290.023
   196.3 2289.09   204.7 2289.22   208.9 2290.06   213.1 2291.46   217.3 2291.74
   248.2 2291.43   259.4 2290.41   321.2 2291.81   343.4 2293.21   356.1 2296.19
   381.4 2296.75     391 2296.36     394 2296.69   406.8 2304.81   420.7 2310.64
#Mann= 3 ,-1,0
       0      .1       0  189.54    .045       0   208.9      .1       0
#XS Ineff= 2 , 0
                          285.71         2303.39
Permanent Ineff=
       F       F
Bank Sta=189.54,208.9
XS Rating Curve= 0 ,0
Exp/Cntr(USF)=0,0
Exp/Cntr=0.3,0.1

Type RM Length L Ch R = 1 ,3675    ,148,163.3,174.3
XS GIS Cut Line= 3
2226280.76194016462033.8393114982226125.46306423461906.580510389
2225887.12242825461891.482008563
#Sta/Elev= 30
       0 2342.14    26.3  2330.5    40.7 2323.78    46.4 2320.62    52.5 2316.46
    60.6 2309.95    71.9 2298.87    77.6 2294.05    83.5    2291      99 2290.21
   114.6 2288.28   133.6  2289.4   165.1 2289.12   186.9 2290.43   222.1 2290.37
   227.22289.094   230.1 2288.32   234.1 2288.18   246.42288.991   254.2 2290.31
   270.2 2289.54   290.2  2291.7   308.9 2291.09   382.4 2292.29   386.4 2292.83
   398.5 2295.98   410.5 2297.23   421.9  2304.3   426.5 2306.64   439.6 2310.41
#Mann= 3 ,-1,0
       0      .1       0   227.2    .045       0   246.4      .1       0
Bank Sta=227.2,246.4
XS Rating Curve= 0 ,0
Exp/Cntr(USF)=0,0
Exp/Cntr=0.3,0.1

Type RM Length L Ch R = 1 ,3512    ,349.6,345.6,340.5
XS GIS Cut Line= 2
2226322.59510829462000.2094482052226105.51749068461690.033909303
#Sta/Elev= 30
       0 2346.59     9.7 2342.42    52.7 2321.95    62.3 2318.44    91.6 2305.44
   101.6 2301.95     116  2296.3   130.6 2289.19   136.8 2288.44   150.2  2288.9
   170.5 2288.92   185.6  2288.1   192.6 2287.03   199.6  2286.4   210.7 2287.22
   220.5 2287.31   245.2 2286.73   252.7 2285.97   257.6 2285.51   268.2 2285.57
   272.2 2285.91   277.1 2286.93     282 2288.74   286.9 2291.67   301.5 2297.79
   311.2 2303.27     340 2316.57     353 2323.77   360.1 2326.77   378.6 2336.12
#Mann= 3 ,-1,0
       0      .1       0   252.7    .045       0   272.2      .1       0
Bank Sta=252.7,272.2
XS Rating Curve= 0 ,0
Exp/Cntr(USF)=0,0
Exp/Cntr=0.3,0.1

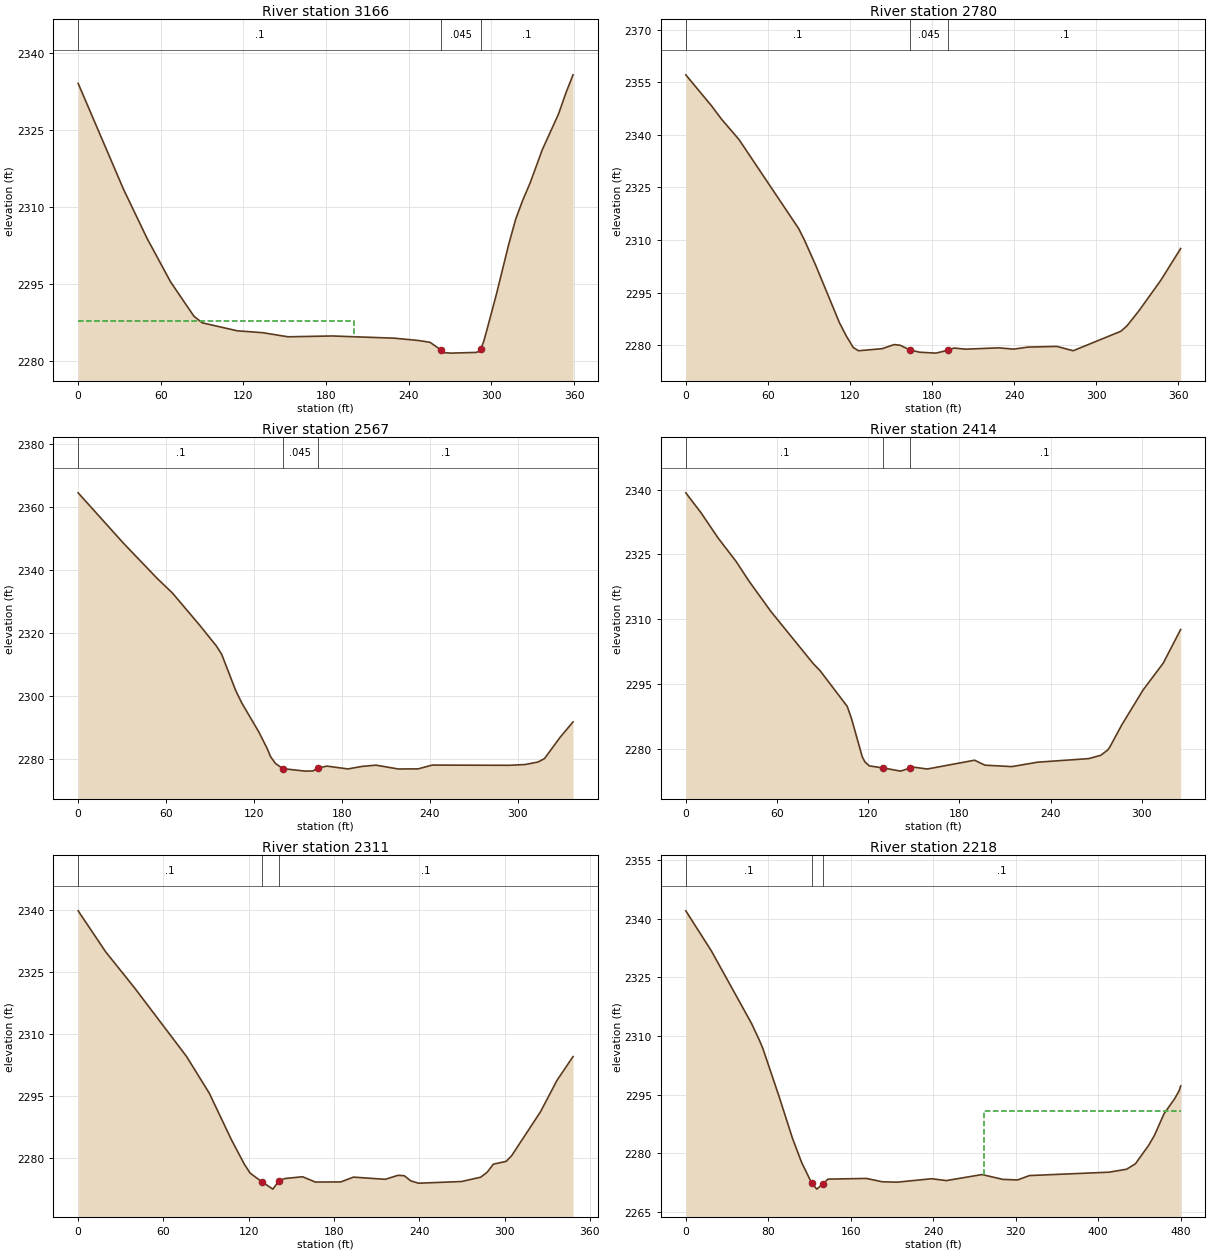
Type RM Length L Ch R = 1 ,3166    ,407,386.4,365.7
XS GIS Cut Line= 2
2226633.28886992461730.482437974 2226356.0736544461501.921321502
#Sta/Elev= 30
       0 2334.16      33 2313.44      50 2303.91    67.1  2295.4    84.1 2288.67
    90.1  2287.4   115.5 2285.84   134.1 2285.47   152.3 2284.67   184.4 2284.83
   229.6  2284.4   247.3 2283.94   255.5 2283.59   263.1 2282.16   265.8 2281.57
     271 2281.48   288.7 2281.62   291.3  2281.8   292.32282.252   294.4 2283.72
   296.9 2286.14   303.9 2293.22   312.5 2302.61   317.7 2307.66   322.7 2311.28
   328.1 2314.68     337 2321.21   348.8  2328.2   354.2 2332.35   359.3 2335.83
#Mann= 3 ,-1,0
       0      .1       0   263.1    .045       0   292.3      .1       0
#XS Ineff= 2 , 0
             200 2287.79
Permanent Ineff=
       F       F
Bank Sta=263.1,292.3
XS Rating Curve= 0 ,0
Exp/Cntr(USF)=0,0
Exp/Cntr=0.3,0.1

Type RM Length L Ch R = 1 ,2780    ,216,213,210.7
XS GIS Cut Line= 2
 2226679.8270814461115.6994257832226348.17471799461260.196442511
#Sta/Elev= 30
       0 2357.16    19.1 2348.17    25.8 2344.65    38.9 2338.68    82.5 2313.27
    86.9 2309.84    95.1 2302.65   112.4 2286.31   117.4 2282.54   122.4 2279.31
   126.2 2278.37   143.6 2278.96   152.3 2280.13   156.7 2279.94   163.9 2278.58
     171 2277.95   182.9 2277.69   191.6 2278.52     196 2279.14   204.7 2278.82
   228.8  2279.2   239.6 2278.83   250.1 2279.41   271.3 2279.61   283.2 2278.37
   318.1 2283.94   322.5 2285.46   331.2 2289.73   347.3  2298.5   361.8 2307.57
#Mann= 3 ,-1,0
       0      .1       0   163.9    .045       0   191.6      .1       0
Bank Sta=163.9,191.6
XS Rating Curve= 0 ,0
Exp/Cntr(USF)=0,0
Exp/Cntr=0.3,0.1

Type RM Length L Ch R = 1 ,2567    ,158.2,152.6,158.7
XS GIS Cut Line= 2
2226553.97092907460916.4023056532226271.86993681461101.995063719
#Sta/Elev= 30
       0 2364.41    30.9 2348.41    53.8 2337.28    64.4 2332.54    82.7 2322.48
    94.3 2315.77    97.9 2313.15   107.5 2301.62   111.6 2297.69   123.2 2288.51
   128.9 2283.26   131.4 2280.51   134.7  2278.4   139.7 2276.78   154.9 2275.99
   160.2 2276.05   163.6 2276.92   169.7 2277.59   184.1 2276.69   193.7 2277.49
   203.2 2277.89   218.5 2276.67     232 2276.71   241.6 2277.91   294.2 2277.84
   305.1 2278.09   313.8 2278.89   318.2 2279.96   328.9 2286.75   337.7 2291.63
#Mann= 3 ,-1,0
       0      .1       0   139.7    .045       0   163.6      .1       0
Bank Sta=139.7,163.6
XS Rating Curve= 0 ,0
Exp/Cntr(USF)=0,0
Exp/Cntr=0.3,0.1

Type RM Length L Ch R = 1 ,2414    ,115.8,103.4,114
XS GIS Cut Line= 2
 2226444.8268612460816.867707067  2226162.668216460979.349156008
#Sta/Elev= 30
       0 2339.28      10 2334.67    21.2 2328.84    33.1 2323.38    41.7 2318.76
    56.1 2311.74    83.8 2299.73    88.5    2298   106.2  2289.8   109.1 2286.88
   116.1 2278.11   117.9  2276.9   120.8    2276     130 2275.52   141.3 2274.79
   147.2 2275.48   150.1  2275.7   158.9 2275.28     190 2277.32   196.8 2276.17
   214.5 2275.84   231.5 2276.86   265.1 2277.69   273.1 2278.47   277.7 2279.72
     279 2280.38   286.9 2285.53   300.8 2293.56   314.1  2299.8   325.6 2307.62
#Mann= 3 ,-1,0
       0      .1       0     130    .045       0   147.2      .1       0
Bank Sta=130,147.2
XS Rating Curve= 0 ,0
Exp/Cntr(USF)=0,0
Exp/Cntr=0.3,0.1

Type RM Length L Ch R = 1 ,2311    ,100,93.2,131
XS GIS Cut Line= 3
2226443.19843642460809.4490280342226291.66649767460781.950663143
2226118.13248022460869.068403222
#Sta/Elev= 30
       0 2339.81    19.3 2329.93    39.7 2321.19    76.2 2304.65    92.3 2295.73
   107.7  2284.6   116.9 2278.61     121 2276.44   129.1 2274.38     137 2272.57
   141.3 2274.56   145.4 2275.13   157.9 2275.56   166.9 2274.28   184.8 2274.31
   193.7 2275.47   216.1 2274.94   225.1 2275.91   229.5  2275.8     234 2274.57
   239.5    2274   269.8 2274.41   283.2 2275.45   287.7 2276.62   292.2 2278.61
   301.1 2279.27     305 2280.64   325.4 2291.31   336.9 2298.84   348.2 2304.59
#Mann= 3 ,-1,0
       0      .1       0   129.1    .045       0   141.3      .1       0
Bank Sta=129.1,141.3
XS Rating Curve= 0 ,0
Exp/Cntr(USF)=0,0
Exp/Cntr=0.3,0.1

Type RM Length L Ch R = 1 ,2218    ,100.5,100.6,99
XS GIS Cut Line= 3
2226440.45908031460768.8221173262226153.05909805 460568.77775277
2226030.76123325460612.455561625
#Sta/Elev= 30
       0 2342.04    24.7 2331.83    63.7 2313.23    71.8 2308.66    74.7 2306.83
    90.4 2294.56   103.4 2283.86   112.4 2277.58   122.2 2272.27   127.1 2270.78
   133.12272.165   137.9 2273.34   175.2 2273.52   190.4 2272.67     205 2272.56
   238.4 2273.44   252.8 2272.97   287.3 2274.51   307.4 2273.28   321.8 2273.13
   333.3 2274.25   410.6 2275.12   427.6 2275.88   436.1 2277.27   448.8 2281.94
   454.5  2284.5   463.8 2290.05   474.3 2293.99   478.5 2295.97     480 2297.19
#Mann= 3 ,-1,0
       0      .1       0   122.2    .045       0   133.1      .1       0
#XS Ineff= 2 , 0
                          289.04         2290.88
Permanent Ineff=
       F       F
Bank Sta=122.2,133.1
XS Rating Curve= 0 ,0
Exp/Cntr(USF)=0,0
Exp/Cntr=0.3,0.1

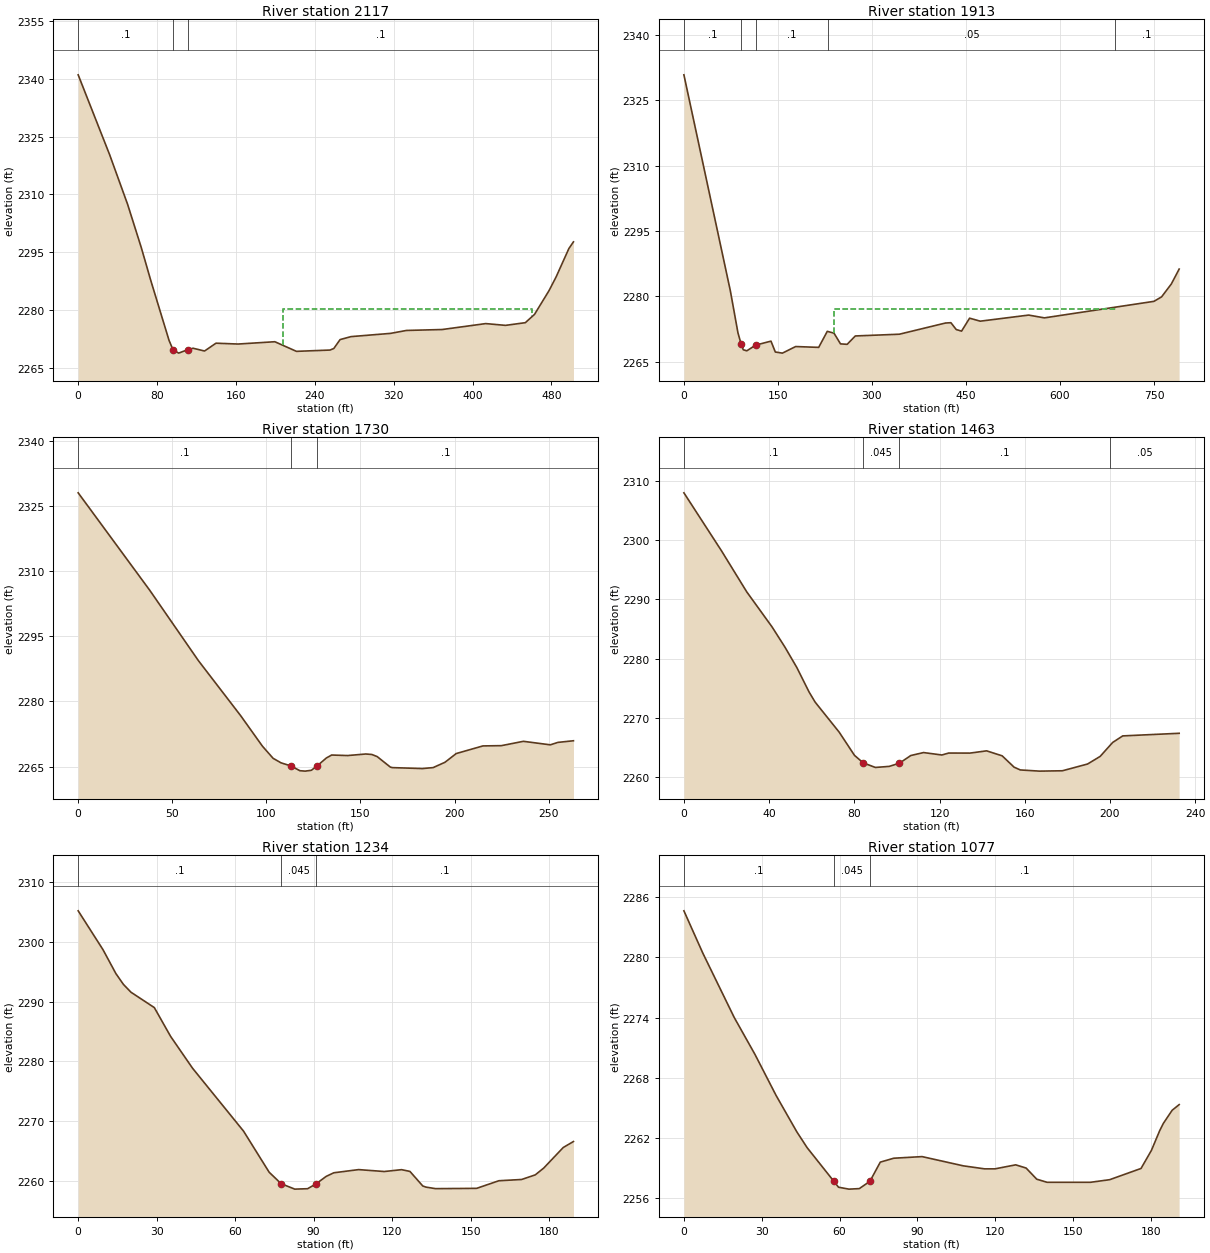
Type RM Length L Ch R = 1 ,2117    ,200,203.8,209.3
XS GIS Cut Line= 3
2226467.19402704460658.0452177372226216.64923943460507.440447519
 2226007.6016115460527.698717428
#Sta/Elev= 30
       0 2341.08      32 2320.27    50.2  2307.4      64 2296.22    73.5 2287.79
    92.2 2272.08    96.1 2269.72   101.9 2268.79   111.6 2269.73   116.5 2270.06
   128.2 2269.34   139.8 2271.37   162.2 2271.15   199.5 2271.75   221.4 2269.25
   255.5 2269.59   259.3 2269.99   265.7 2272.31   276.8 2273.08   316.9 2273.92
     333 2274.68   369.2 2274.92   413.4 2276.46   433.5    2276   453.6  2276.7
   462.9 2278.85   477.7 2285.05   484.9 2288.63   497.8 2295.97   502.4 2297.69
#Mann= 3 ,-1,0
       0      .1       0    96.1    .045       0   111.6      .1       0
#XS Ineff= 1 ,-1
  207.52   460.62280.177
Permanent Ineff=
       F
Bank Sta=96.1,111.6
XS Rating Curve= 0 ,0
Exp/Cntr(USF)=0,0
Exp/Cntr=0.3,0.1

Type RM Length L Ch R = 1 ,1913    ,184.2,182.8,179.8
XS GIS Cut Line= 3
2226572.56195263460522.3896853182226345.56521538460259.041083636
2225930.31634296460411.405286855
#Sta/Elev= 30
       0 2330.86    74.1 2281.29    86.2 2271.6791.338442269.049    94.7 2267.77
   100.4 2267.53114.42292268.837   138.9 2269.75   145.8 2267.26   157.1    2267
   178.3 2268.51     215 2268.32   228.7    2272   239.4 2271.58   249.8 2269.12
   260.4 2269.02   273.4 2270.94   343.7 2271.34   417.3 2273.91   425.9 2273.98
   434.4 2272.41   442.9 2272.05   455.7 2275.02   472.7 2274.33   549.9 2275.73
     575 2275.09   749.7 2278.88   761.9  2279.9   777.5 2282.87     790 2286.29
#Mann= 5 ,-1,0
       0      .1       091.33844    .045       0114.4229      .1       0
     230     .05       0  687.68      .1       0
#XS Ineff= 1 ,-1
  239.38   689.6 2277.03
Permanent Ineff=
       T
Bank Sta=91.33844,114.4229
XS Rating Curve= 0 ,0
Exp/Cntr(USF)=0,0
Exp/Cntr=0.3,0.1

Type RM Length L Ch R = 1 ,1730    ,266,267.3,268.4
XS GIS Cut Line= 2
2226704.53902503460383.0805533382226508.36242891 460207.61903706
#Sta/Elev= 30
       0 2328.08    38.1 2305.58    63.9  2289.4    86.4 2276.69    97.9  2269.7
   103.6 2266.89   107.8 2265.85   113.2 2265.12   117.8 2264.04   120.6 2263.94
   123.9 2264.13  127.072265.178   131.9 2266.97   134.7 2267.65   143.2 2267.53
   152.9 2267.89   156.1 2267.77   158.9 2267.29   165.9 2264.87   166.9 2264.75
   182.9 2264.53   188.6 2264.75   194.9 2265.97   200.9 2267.99   215.1 2269.75
   224.9 2269.81   236.6 2270.81   250.9    2270   254.9 2270.56   263.2 2270.94
#Mann= 3 ,-1,0
       0      .1       0   113.2    .045       0  127.07      .1       0
Bank Sta=113.2,127.07
XS Rating Curve= 0 ,0
Exp/Cntr(USF)=0,0
Exp/Cntr=0.3,0.1

Type RM Length L Ch R = 1 ,1463    ,231.4,228.8,225.8
XS GIS Cut Line= 2
2226852.09672404460172.2838404732226695.15268128460000.805171374
#Sta/Elev= 30
       0 2307.96    17.7 2298.15    29.5 2291.26    41.4 2285.34    47.4 2281.96
      53 2278.51    58.8 2274.35    61.6 2272.67    72.9  2267.6    80.1 2263.68
    84.2 2262.42    89.9 2261.65    96.4 2261.83   101.2 2262.37   106.5 2263.66
   112.5 2264.16   121.1 2263.75   124.3 2264.08   134.3 2264.07   142.1 2264.45
   149.4 2263.61     155  2261.7   157.9 2261.23   166.9 2261.03   177.7 2261.09
   189.5 2262.23   195.4 2263.51   201.3 2265.87     206 2266.97   232.5 2267.41
#Mann= 4 ,-1,0
       0      .1       0    84.2    .045       0   101.2      .1       0
     200     .05       0
Bank Sta=84.2,101.2
XS Rating Curve= 0 ,0
Exp/Cntr(USF)=0,0
Exp/Cntr=0.3,0.1

Type RM Length L Ch R = 1 ,1234    ,165,157.8,153.1
XS GIS Cut Line= 2
2226999.98029236459973.4730083352226845.02739054459864.814766747
#Sta/Elev= 30
       0 2305.16     9.5 2298.66    14.4 2294.69    17.3 2292.87    20.2 2291.56
    29.1    2289    35.3 2284.21    43.7 2278.88    63.2 2268.37      73  2261.5
    77.6 2259.58    82.8 2258.68    87.7 2258.75    90.92259.555    94.8 2260.81
    97.7 2261.41   107.2 2261.94     117 2261.62   123.6 2261.93   126.8 2261.64
   131.7 2259.21   132.9 2259.02   136.6 2258.76   152.3 2258.81   160.8 2260.08
   169.5 2260.29   174.7 2261.06   177.9 2262.18   185.4 2265.63   189.3 2266.63
#Mann= 3 ,-1,0
       0      .1       0    77.6    .045       0    90.9      .1       0
Bank Sta=77.6,90.9
XS Rating Curve= 0 ,0
Exp/Cntr(USF)=0,0
Exp/Cntr=0.3,0.1

Type RM Length L Ch R = 1 ,1077    ,79.1,89.4,112
XS GIS Cut Line= 2
2227055.48957819459787.8457381222226865.47228877459769.204801502
#Sta/Elev= 30
       0 2284.65     7.3 2280.43    19.4 2274.02    27.4 2270.34    35.5 2266.27
    43.5 2262.64    47.5 2261.05   57.772257.709    59.6 2257.11    63.6 2256.92
    67.6 2256.97    71.7  2257.7    75.7 2259.61    80.9    2260    91.8 2260.16
   107.7 2259.24   115.9 2258.94   119.9 2258.94   127.9 2259.34   131.9 2259.02
     136 2257.91     140  2257.6   156.7  2257.6   164.1 2257.86   176.2 2258.98
   180.2 2260.78   183.4 2262.75   184.8 2263.47   188.2 2264.78   190.9 2265.34
#Mann= 3 ,-1,0
       0      .1       0   57.77    .045       0    71.7      .1       0
Bank Sta=57.77,71.7
XS Rating Curve= 0 ,0
Exp/Cntr(USF)=0,0
Exp/Cntr=0.3,0.1

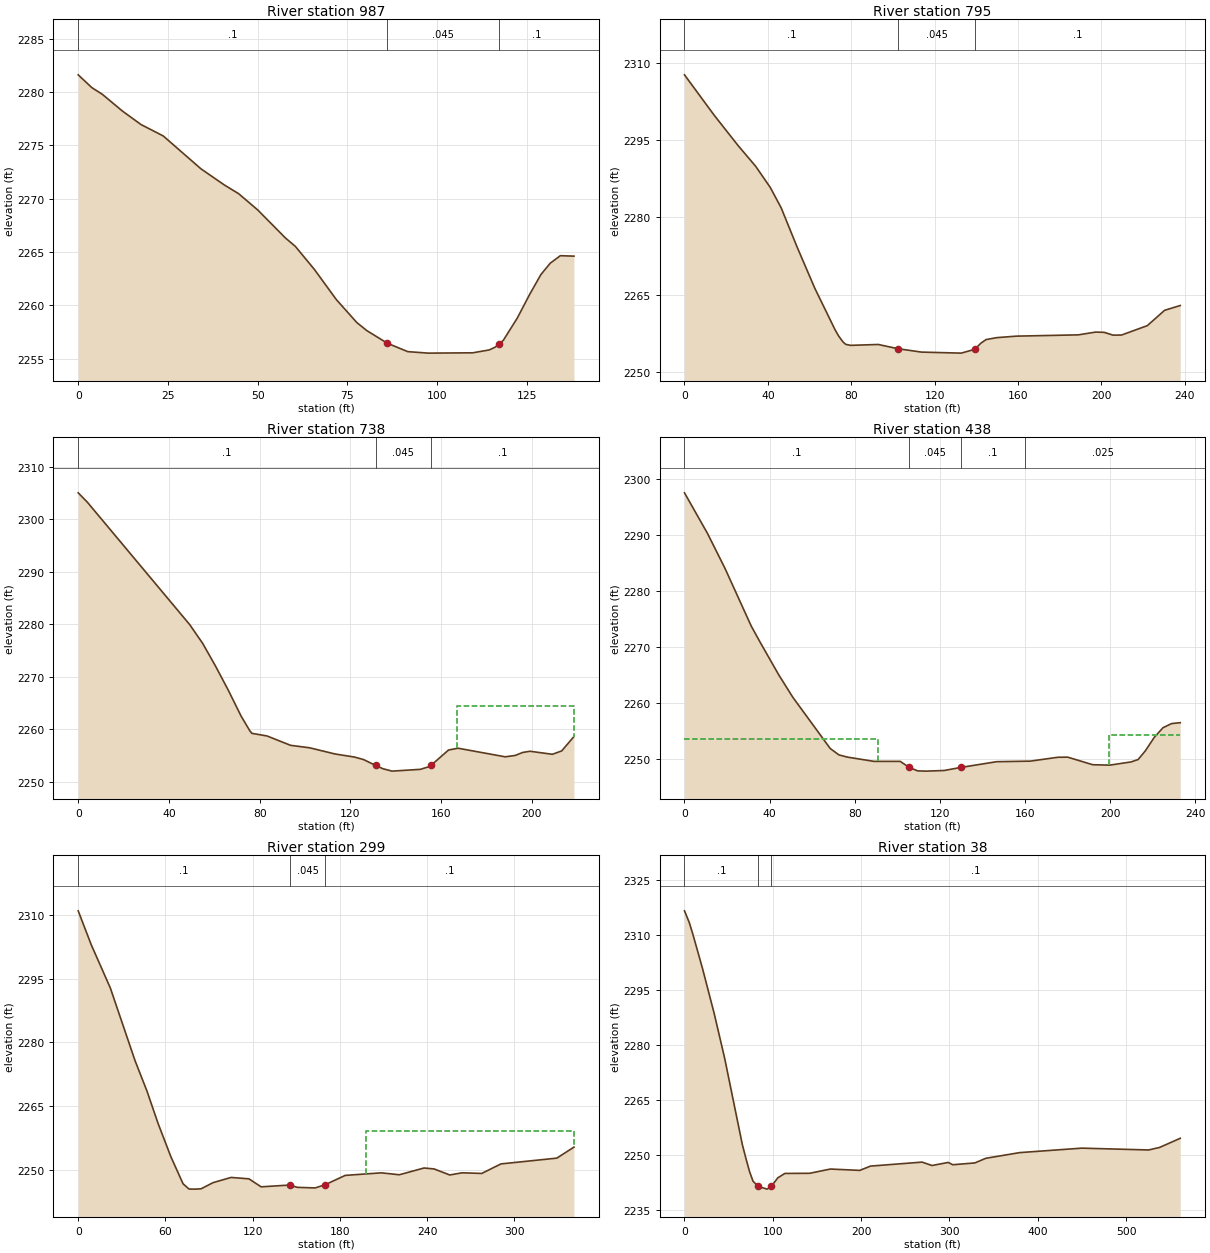
Type RM Length L Ch R = 1 ,987     ,194.7,192.5,187.3
XS GIS Cut Line= 2
2227055.56137732459767.1875487942226965.89281831 459662.16974607
#Sta/Elev= 30
       0 2281.61     3.8 2280.41     6.7 2279.79    12.3 2278.22    17.5 2276.95
    23.7 2275.88    34.2  2272.8    40.7 2271.29    44.7 2270.47      50 2268.95
    57.7 2266.33    60.5 2265.53    65.8 2263.37    71.9 2260.55    77.6  2258.4
    80.4 2257.64    86.1 2256.46    91.8 2255.67    97.5 2255.53   109.9 2255.56
   114.5 2255.83   116.1 2256.08   117.3  2256.4   118.4 2256.72   122.3 2258.81
   125.8 2261.06   128.9  2262.9   131.5 2263.96   134.3 2264.66   138.1 2264.62
#Mann= 3 ,-1,0
       0      .1       0    86.1    .045       0   117.3      .1       0
Bank Sta=86.1,117.3
XS Rating Curve= 0 ,0
Exp/Cntr(USF)=0,0
Exp/Cntr=0.3,0.1

Type RM Length L Ch R = 1 ,795     ,67.3,56.9,48.4
XS GIS Cut Line= 3
2227204.03558378459621.4628646832227080.74504071459520.258099543
2227004.90518586459540.054823888
#Sta/Elev= 30
       0 2307.68    14.3 2299.81    25.7 2293.95    34.2 2289.89    41.2 2285.78
    46.4 2281.84    54.1 2274.17    62.6 2266.16    72.3 2258.12      74 2256.92
    76.1 2255.77    77.4 2255.31    79.7 2255.12      93 2255.29   102.52254.463
   113.7 2253.81   132.8 2253.61  139.312254.352   142.2 2255.53   144.7 2256.24
   149.9 2256.62   159.3 2256.91     189 2257.16   197.3  2257.7   201.4 2257.65
   205.6 2257.11   209.7 2257.12   222.1 2258.95   230.4 2261.93   237.9 2262.86
#Mann= 3 ,-1,0
       0      .1       0   102.5    .045       0  139.31      .1       0
Bank Sta=102.5,139.31
XS Rating Curve= 0 ,0
Exp/Cntr(USF)=0,0
Exp/Cntr=0.3,0.1

Type RM Length L Ch R = 1 ,738     ,303,299.8,282.8
XS GIS Cut Line= 3
2227242.97697025459574.6934483342227170.18816386459501.904641944
2227058.99896355459470.381930515
#Sta/Elev= 30
       0 2305.06       4 2303.29    49.2  2279.9    54.9 2276.32    60.5 2272.04
    66.2 2267.38    71.8 2262.48    75.7 2259.64    76.6 2259.19    83.2  2258.7
    93.6 2256.91     102 2256.44   113.3 2255.25   121.7 2254.68   125.8 2254.19
   131.1 2253.07   134.3 2252.45   138.3 2251.99   150.8 2252.33   154.9 2252.88
  155.57 2253.12   163.2 2256.01   167.4 2256.36   188.2 2254.72   192.6 2254.98
   195.9 2255.55   199.1 2255.78     209  2255.2   213.1 2255.85   218.5 2258.59
#Mann= 3 ,-1,0
       0      .1       0   131.1    .045       0  155.57      .1       0
#XS Ineff= 2 , 0
                          166.94         2264.49
Permanent Ineff=
       F       F
Bank Sta=131.1,155.57
XS Rating Curve= 0 ,0
Exp/Cntr(USF)=0,0
Exp/Cntr=0.3,0.1

Type RM Length L Ch R = 1 ,438     ,138.7,138.6,138.4
XS GIS Cut Line= 2
 2227262.6920604459174.2072304312227036.31472093459229.197677265
#Sta/Elev= 30
       0 2297.49    10.8 2290.27    19.1 2283.98    31.4 2273.73    35.5 2270.91
    44.3 2265.06    50.9 2261.07    68.5 2251.93    72.6 2250.79    76.7 2250.39
      89 2249.64   101.4 2249.64   105.5 2248.58   109.6 2247.94   113.7  2247.9
     122 2248.01   129.9 2248.56   146.7 2249.58   162.5 2249.68   175.5 2250.37
   180.1 2250.39   191.9 2249.04   199.9 2248.97   209.9 2249.54   213.2 2249.97
   216.5 2251.47   220.8 2253.92   224.9 2255.64     229 2256.38     233 2256.53
#Mann= 4 ,-1,0
       0      .1       0   105.5    .045       0   129.9      .1       0
     160    .025       0
#XS Ineff= 2 , 0
           90.85 2253.62  199.58         2254.34
Permanent Ineff=
       F       F
Bank Sta=105.5,129.9
XS Rating Curve= 0 ,0
Exp/Cntr(USF)=0,0
Exp/Cntr=0.3,0.1

Type RM Length L Ch R = 1 ,299     ,261.4,261.4,261.4
XS GIS Cut Line= 3
  2227258.007689459032.1485761092227029.50291959 459090.75403092
2226957.93636183459167.600582098
#Sta/Elev= 30
       0 2310.96     8.9 2303.04    22.1 2292.81    39.1 2275.71    47.3 2268.56
    54.9 2260.98    63.8 2253.07    72.1 2246.77    76.2 2245.53    80.4 2245.51
    84.5 2245.59    92.7 2247.03   105.1 2248.26   117.4 2247.93   125.8 2246.05
   145.5 2246.47   150.6 2245.93   162.9 2245.79     170 2246.57   183.6 2248.74
   208.4 2249.34   220.8 2248.89   237.8 2250.48   244.7 2250.26   255.5 2248.84
     264 2249.35   277.5  2249.2   290.7 2251.44   329.1  2252.8   340.9 2255.39
#Mann= 3 ,-1,0
       0      .1       0   145.5    .045       0     170      .1       0
#XS Ineff= 2 , 0
                          197.67         2259.12
Permanent Ineff=
       F       F
Bank Sta=145.5,170
XS Rating Curve= 0 ,0
Exp/Cntr(USF)=0,0
Exp/Cntr=0.3,0.1

Type RM Length L Ch R = 1 ,38      ,,,
XS GIS Cut Line= 4
2227253.52698593 458829.600430272227135.29752523458820.435355797
2226980.47165698458912.2299465482226903.21370112459163.480698827
#Sta/Elev= 30
       0 2316.58     5.4 2313.41     9.4 2310.28    20.3 2300.96    33.5 2288.72
    45.5 2276.37    65.5 2252.84    69.6 2249.03    73.6 2245.52    77.6 2242.84
    83.6 2241.42    93.6 2240.67    98.5 2241.46   105.7 2243.76   113.7 2244.95
   141.8 2244.99   165.2 2246.15   198.5 2245.78   210.6 2246.95   269.1 2248.04
   280.3 2247.11   298.6 2247.95   303.8 2247.32   328.9 2247.82   341.2 2249.08
   379.6 2250.63     450 2251.85   525.6 2251.35   538.1 2252.05   561.4 2254.54
#Mann= 3 ,-1,0
       0      .1       0    83.6    .045       0    98.5      .1       0
Bank Sta=83.6,98.5
XS Rating Curve= 0 ,0
Exp/Cntr(USF)=0,0
Exp/Cntr=0.3,0.1
LCMann Table=0

Chan Stop Cuts=-1
Use User Specified Reach Order=0
Composite Channel Slope=5